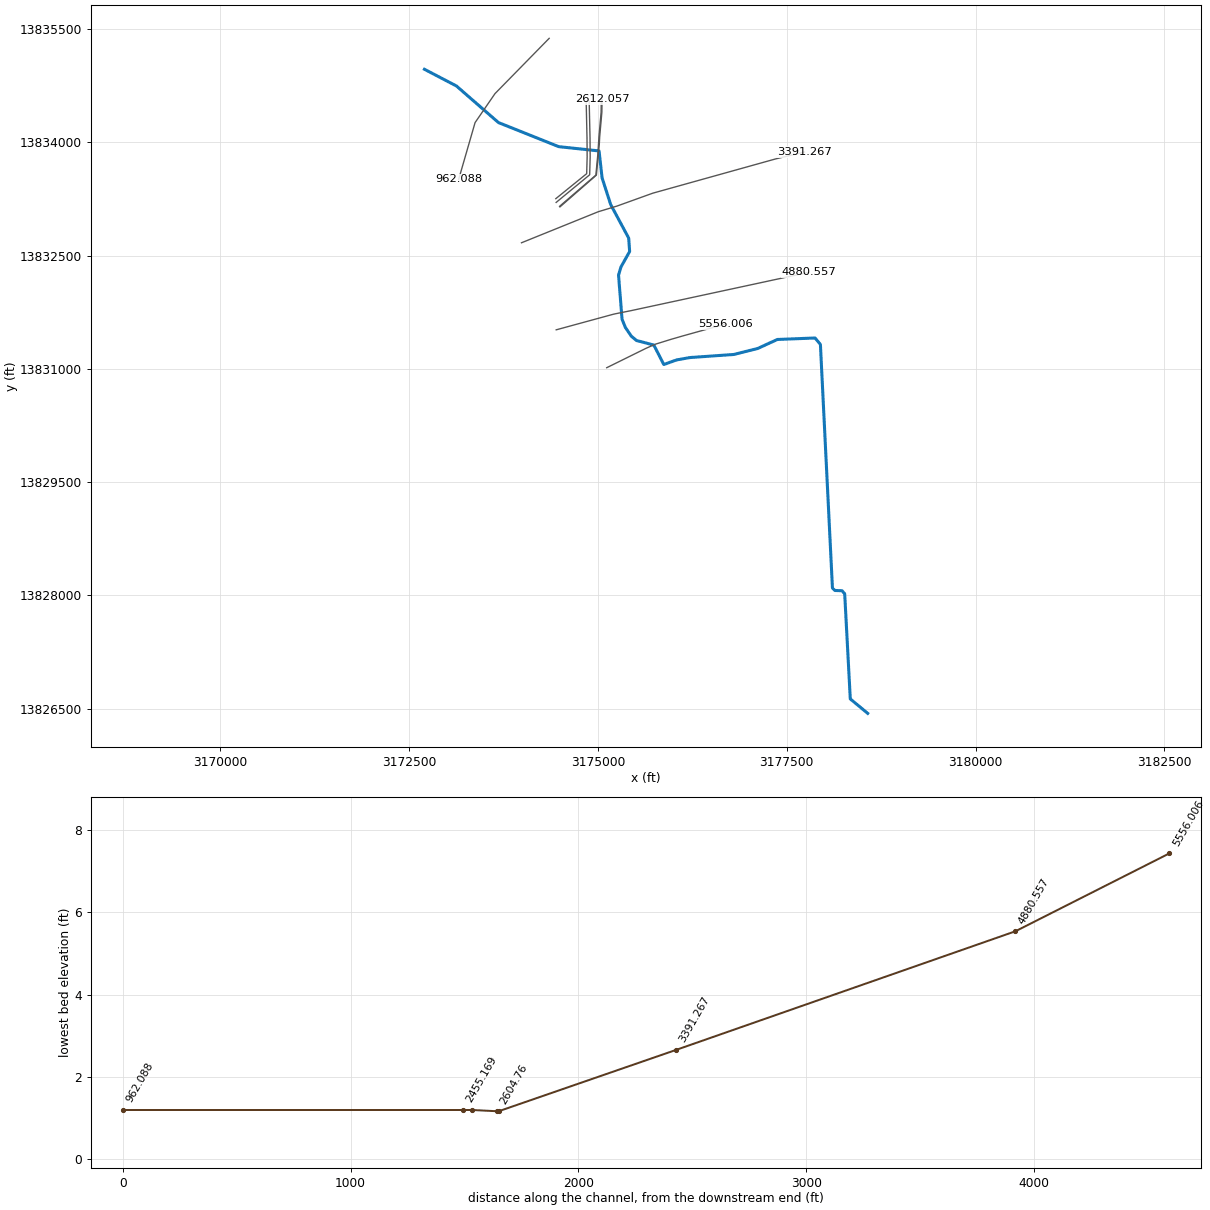
--- G110_00_00.prj (project) ---

Proj Title=G110-00-00
Current Plan=p04
Default Exp/Contr=.3,.1
English Units
Geom File=g01
Geom File=g02
Flow File=f04
Flow File=f05
Plan File=p04
Plan File=p05
Y Axis Title=Elevation
X Axis Title(PF)=Main Channel Distance
X Axis Title(XS)=Station
BEGIN DESCRIPTION:
San Jacinto
Buffalo Bayou Trib. 8.17
HCFCD Unit G110-00-00
Flood Hazard Model
10, 2, 1, 0.2% Event
Filename G110-00-00.prj
Prepared by: Matthew Fischer Date: 5-25-04
Reviewd by:		Date:
Status Final Submittal
END DESCRIPTION:
DSS Export Rating Curves= 0
DSS Export Rating Curve Sorted= 0
DSS Export Volume Flow Curves= 0
DXF OffsetX= 0
DXF OffsetY= 0
DXF ScaleX= 1
DXF ScaleY= 10

--- G110_00_00.p04 (plan) ---

Plan Title=FEMA Effective June 2007
Version=Version 3.0.1  Mar 2001
Short Identifier=FEMAeff0607
Geom File=g01
Flow File=f04
Subcritical Flow
K Sum by GR= 0
Std Step Tol= 0.01
Critical Tol= 0.01
Num of Std Step Trials= 20
Max Error Tol= 0.3
Flow Tol Ratio= 0.001
Split Flow NTrial= 30
Split Flow Tol= 0.02
Split Flow Ratio= 0.02
Log Output Level= 0
Friction Slope Method= 1
Unsteady Friction Slope Method= 2
Parabolic Critical Depth
Global Vel Dist= 0 , 0 , 0
Global Log Level= 0
CheckData=True
Encroach Param=-1 ,0,0, 0
Computation Interval=1HOUR
Output Interval=1HOUR
Run HTab= 0
Run UNet= 0
Run PostProcess= 0
UNET Theta= 1
UNET ZTol= 0.02
UNET ZSATol= 0.1
UNET MxIter= 20
UNET MaxInSteps= 20
UNET DtIC= 0
UNET DtMin= 0
UNET MaxCRTS= 20
UNET WFStab= 2
UNET SFStab= 1
UNET WFX= 1
UNET SFX= 1
UNET Convert EG Bridges=-1
UNET Use Existing IB Tables=-1
Instantaneous Interval=1HOUR
Write IC File= 0
Write Velocity= 0
Write Detailed= 0

--- G110_00_00.p05 (plan) ---

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Plan Title=Floodway
Short Identifier=Floodway0607
Geom File=g01
Flow File=f04
Encroach Param=-1 ,0,0, 2
Encroach River=G110-00-00
Encroach Reach=G110-00-00_0010
Encroach Node=5556.006
       1  4972.4 5030.48
Encroach Node=4880.557
       1  4892.1  5125.8
Encroach Node=3391.267
       1 4959.64    5139
Encroach Node=2612.057
       1    4886    5037
Encroach Node=2604.76
       1 4893.48    5037
Encroach Node=2550
       1    4400    5600
Encroach Node=2496.072
       1 4879.24 5116.45
Encroach Node=2455.169
       1 4883.53 5123.13
Encroach Node=962.088
       1 4845.52 5150.54

--- G110_00_00.f04 (steady flow) ---

Flow Title=FEMA Effective June 2007
Version=Version 3.0.1  Mar 2001
Number of Profiles= 2
Profile Names= 1PCT_100yr,FW
River Rch & RM=G110-00-00,G110-00-00_0010 ,5556.006
    1817    1817
River Rch & RM=G110-00-00,G110-00-00_0010 ,4880.557
    1754    1754
River Rch & RM=G110-00-00,G110-00-00_0010 ,3391.267
    1716    1716
Boundary for River Rch & Prof#=G110-00-00,G110-00-00_0010 , 1
Up Type= 0
Dn Type= 3
Dn Slope=.0021
DSS Import GetInterval= 0
DSS Import GetPeak= 0
DSS Import FillOption= 0

--- G110_00_00.f05 (steady flow) ---

Flow Title=Floodway
Version=Version 3.0.1  Mar 2001
Number of Profiles= 2
Profile Names=1PCT_100yr, 1PCTFloodway_100yrFW
River Rch & RM=G110-00-00,G110-00-00_0010      ,5556.006
    1817    1817
River Rch & RM=G110-00-00,G110-00-00_0010      ,4880.557
    1754    1754
River Rch & RM=G110-00-00,G110-00-00_0010      ,3391.267
    1716    1716
Boundary for River Rch & Prof#=G110-00-00,G110-00-00_0010      , 1
Up Type= 0
Dn Type= 3
Dn Slope=.0021
DSS Import GetInterval= 0
DSS Import GetPeak= 0
DSS Import FillOption= 0

--- G110_00_00.g01 (geometry) ---

Geom Title=G110-00-00 June 2007
Version=Version 3.0.1  Mar 2001

River Reach=G110-00-00       ,G110-00-00_0010
Reach XY= 30
     3178571.985    13826437.538      3178341.25       13826629.
      3178267.25       13828021.      3178232.25       13828062.
       3178137.5       13828065.        3178105.       13828097.
       3177945.5       13831324.     3177874.518    13831409.157
     3177375.878    13831389.525       3177114.5       13831270.
      3176799.75       13831191.     3176217.619    13831150.021
     3176040.936     13831118.61      3175871.25       13831058.
     3175739.455    13831315.534     3175510.238    13831375.855
     3175442.377    13831431.651     3175363.961     13831546.26
      3175318.72    13831656.344     3175271.972    13832241.451
     3175303.601    13832348.433     3175418.961    13832554.868
     3175406.265    13832732.537     3175168.023    13833176.339
        3175054.       13833530.     3175014.083    13833886.606
      3174481.25       13833943.        3173682.       13834262.
      3173124.75       13834747.       3172701.5       13834968.

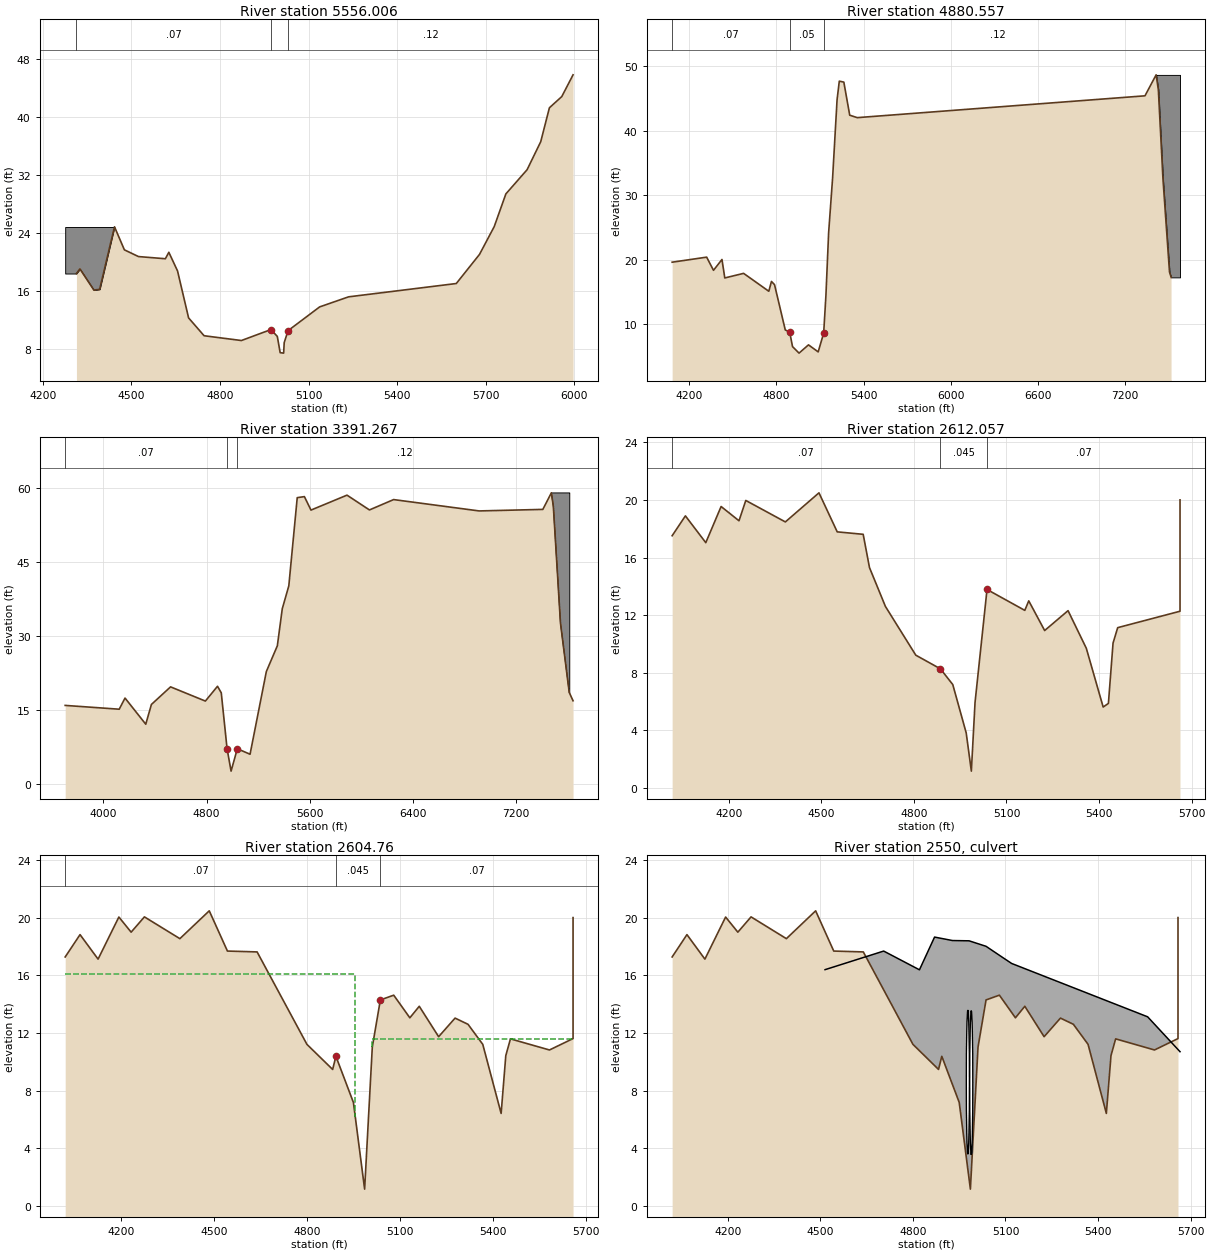
Type RM Length L Ch R = 1 ,5556.006,638.88,675.45,643.07
XS GIS Cut Line= 6
       3175115.4    13831015.447     3175636.038    13831272.512
      3175759.99    13831326.934     3175968.092    13831391.635
     3176126.631    13831437.494     3176687.977    13831593.688
#Sta/Elev= 30
 4313.88   18.42 4325.67   19.05 4372.99   16.13 4392.58   16.24 4442.77   24.87
 4476.23   21.69 4524.03   20.76 4615.07   20.46 4626.79   21.35 4656.29   18.77
  4693.7   12.29 4746.15    9.83 4872.52    9.17  4972.4   10.68 4994.05    9.74
  5003.8    7.49 5015.54    7.43 5017.42    8.88 5030.48   10.53 5137.38   13.81
 5235.33    15.2 5600.16   17.04 5678.76   21.06 5728.62    24.9 5768.02   29.41
 5839.89   32.75    5886   36.61 5915.46    41.3 5957.37   42.85 5995.54   45.85
#Mann= 3 ,-1 , 0
 4313.88     .07       0  4972.4     .05       0 5030.48     .12       0
#Block Obstruct= 1 ,-1
 4275.78 4442.59   24.84
Bank Sta=4972.4,5030.48
XS Rating Curve= 0
Exp/Cntr=.3,.1

Type RM Length L Ch R = 1 ,4880.557,1403.69,1489.29,1467.12
XS GIS Cut Line= 6
     3174446.506    13831517.362     3175196.476    13831721.898
     3175223.441    13831728.398     3175438.617    13831771.478
     3177716.318    13832262.459     3177792.033    13832278.718
#Sta/Elev= 30
 4083.66   19.62  4321.1    20.4    4368   18.36 4426.34   20.04 4445.74   17.18
 4575.02   17.89 4748.48   15.12 4766.66   16.64 4787.78   16.14 4861.68    9.13
  4892.1    8.79 4911.58    6.55 4956.44    5.54 5021.32    6.82 5087.98    5.73
  5125.8    8.64 5141.14   14.43 5159.78   24.15 5187.18   32.66 5217.88   44.78
 5233.22   47.65 5264.48    47.5 5304.86   42.38 5356.72      42 7335.42   45.38
 7412.14   48.63 7427.48   46.31 7459.06   32.54  7504.2   18.09 7515.66   17.27
#Mann= 3 ,-1 , 0
 4083.66     .07       0  4892.1     .05       0  5125.8     .12       0
#Block Obstruct= 1 ,-1
 7412.49 7576.43   48.62
Bank Sta=4892.1,5125.8
XS Rating Curve= 0
Exp/Cntr=.3,.1

Type RM Length L Ch R = 1 ,3391.267,365.39,779.21,1125.8
XS GIS Cut Line= 6
     3173986.716    13832670.181     3175003.502    13833081.409
     3175253.125    13833156.924     3175725.613    13833327.074
     3177354.839     13833781.49     3177734.608    13833871.595
#Sta/Elev= 30
 3703.16   15.98 4122.52   15.21 4167.66   17.47 4328.52   12.17 4372.36   16.17
 4521.04   19.74 4791.24   16.86 4885.38   19.86 4914.58   18.53 4959.64     7.2
  4990.7    2.66 5039.26     7.2 5138.06    6.08 5264.46   22.85 5349.78   28.06
 5388.06   35.57 5438.84   40.22 5504.16   58.09 5559.84    58.3 5610.84   55.57
 5890.46    58.6 6064.62    55.6 6252.18    57.7 6915.96    55.4 7410.42   55.71
  7476.6   59.07 7492.02    56.3 7547.18   32.68 7615.36    18.6 7644.94   16.92
#Mann= 3 ,-1 , 0
 3703.16     .07       0 4959.64     .05       0 5039.26     .12       0
#XS Ineff= 1 ,-1
 4174.84 4395.51   15.99
Permanent Ineff=
       F
#Block Obstruct= 3 ,-1
 7476.12 7619.35   59.05
Bank Sta=4959.64,5039.26
XS Rating Curve= 0
Exp/Cntr=.3,.1

Type RM Length L Ch R = 1 ,2612.057,6.73,7.3,11.07
BEGIN DESCRIPTION:
Access Road
END DESCRIPTION:
XS GIS Cut Line= 6
     3174496.407    13833145.837      3174978.68    13833566.164
     3175017.082    13833973.398     3175022.419     13834073.58
     3175051.181    13834398.676     3175053.497     13834569.62
#Sta/Elev= 30
 4016.24   17.51  4059.2   18.89 4125.32   17.03 4174.98   19.54 4232.96   18.55
 4254.98   19.96 4383.24   18.47 4492.24   20.49  4551.4   17.78 4635.58   17.61
 4655.98    15.3 4707.72    12.6  4806.1    9.22    4886    8.27    4926    7.18
 4969.55    3.82 4986.22    1.17 4998.18    5.94    5037   13.78 5159.48   12.33
  5172.3   12.99 5223.84   10.93 5299.72   12.31 5358.88     9.7 5413.52    5.62
 5430.52    5.87 5445.58   10.06 5460.64   11.13 5662.68   12.27 5662.68      20
#Mann= 3 ,-1 , 0
 4016.24     .07       0    4886    .045       0    5037     .07       0
Bank Sta=4886,5037
XS Rating Curve= 0
Exp/Cntr=.5,.3

Type RM Length L Ch R = 1 ,2604.76 ,62.31,108.69,151.12
BEGIN DESCRIPTION:
Access Road
END DESCRIPTION:
XS GIS Cut Line= 6
     3174491.152    13833152.843      3174971.62    13833566.165
     3174998.555    13833850.519     3175012.442    13834074.287
     3175041.187    13834399.185     3175043.498    13834569.756
#Sta/Elev= 30
 4019.06   17.27 4067.04   18.82  4125.3   17.12 4192.46   20.04  4232.1   18.99
 4274.96   20.05 4389.52   18.54  4484.4   20.47  4543.1   17.68 4638.98   17.62
 4799.86   11.21 4882.92    9.47 4893.48   10.38    4950    7.18 4986.22    1.17
    5011   11.02    5037   14.29 5080.22   14.62  5132.3   13.05  5162.7   13.85
 5225.26   11.74 5278.34   13.03  5320.2    12.6  5367.8   11.21 5427.12    6.42
 5442.18   10.43 5457.24   11.59 5583.26   10.82 5659.42   11.61 5659.42      20
#Mann= 3 ,-1 , 0
 4019.06     .07       0 4893.48    .045       0    5037     .07       0
#XS Ineff= 2 , 0
       0    4956    16.1    5011       0    11.6
Permanent Ineff=
       F       F
Bank Sta=4893.48,5037
XS Rating Curve= 0
Exp/Cntr=.5,.3

Type RM Length L Ch R = 2 ,2550    ,,,
BEGIN DESCRIPTION:
2 CMP's @ Access Road
END DESCRIPTION:
Bridge Culvert--1,0,-1,-1, 0
Deck Dist Width WeirC Skew NumUp NumDn MinLoCord MaxHiCord MaxSubmerge Is_Ogee
35,27,2.6,0, 11, 10, , , .95, 0, 0,0,,
    4515    4705    4821    4870    4928    4982    5037    5087    5120    5561
    5666
   16.39   17.68   16.38   18.65   18.41   18.39   18.01   17.29   16.82   13.12
    10.7
       0       0       0       0       0       0       0       0       0       0
       0
    4705    4821    4870    4928    4982    5037    5087    5120    5561    5666
   17.68   16.38   18.65   18.41   18.39   18.01   17.29   16.82   13.12    10.7
       0       0       0       0       0       0       0       0       0       0
Culvert=1,10,,59,.024,.9,1,2,3,3.59,4978,2.75,4969,Culvert #2  , 0 ,17
Culvert Bottom n=.024
Culvert=1,10,,59,.024,.9,1,2,3,3.55,4989,2.71,4980,Culvert #1  , 0 ,17
Culvert Bottom n=.024
BC Design=,, 0 ,, 0 ,,,,,,

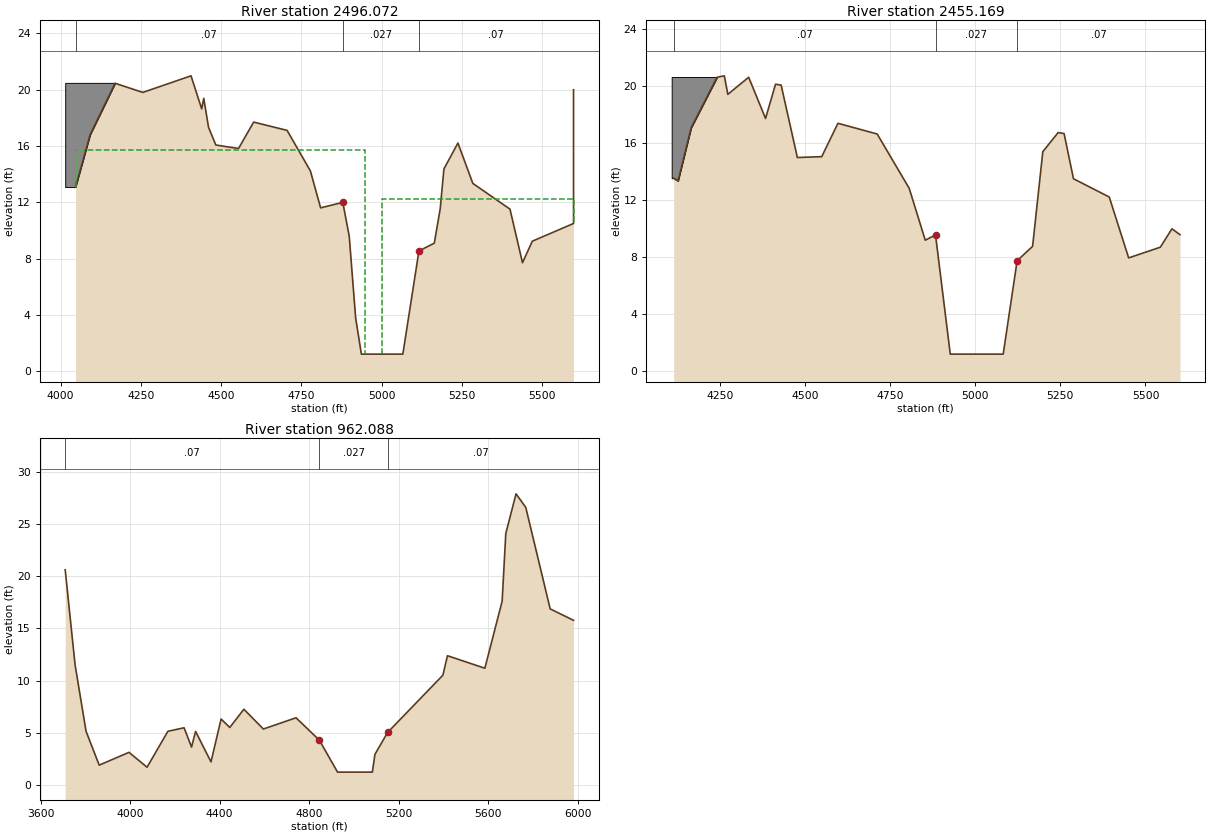
Type RM Length L Ch R = 1 ,2496.072,38.41,40.9,40.72
BEGIN DESCRIPTION:
Access Road
END DESCRIPTION:
XS GIS Cut Line= 5
     3174445.839    13833204.611      3174889.72    13833570.895
     3174896.279    13833808.365     3174894.363    13834058.818
     3174883.271     13834546.28
#Sta/Elev= 30
 4046.85   13.08 4092.21    16.8    4170   20.46 4256.27   19.81 4406.48   20.99
 4439.72   18.64  4446.1   19.39 4461.03   17.33 4483.78   16.07 4554.48   15.82
 4601.61    17.7  4705.7   17.11 4778.29   14.23 4810.14    11.6 4879.24   11.99
 4899.32    9.58 4919.24    3.78 4937.13     1.2 5066.27     1.2 5116.45    8.54
 5164.26    9.09 5182.71   11.54 5194.27   14.37 5237.87   16.21 5284.29   13.34
 5399.97   11.51 5438.98     7.7 5469.58    9.23 5597.95   10.49 5597.95      20
#Mann= 3 ,-1 , 0
 4046.85     .07       0 4879.24    .027       0 5116.45     .07       0
#XS Ineff= 2 , 0
       0    4947    15.7    5002       0    12.2
Permanent Ineff=
       F       F
#Block Obstruct= 1 ,-1
 4014.58 4169.57   20.49
Bank Sta=4879.24,5116.45
XS Rating Curve= 0
Exp/Cntr=.5,.3

Type RM Length L Ch R = 1 ,2455.169,290.84,1493.08,163.74
BEGIN DESCRIPTION:
Access Road
END DESCRIPTION:
XS GIS Cut Line= 5
     3174440.888    13833254.121     3174850.111    13833585.611
     3174856.275    13833808.764     3174854.367     13834058.21
     3174843.281     13834545.37
#Sta/Elev= 30
 4114.72   13.54 4127.51   13.35 4166.12   17.08 4242.25   20.62 4263.39   20.72
 4273.64   19.42 4334.88   20.62 4384.39   17.73 4413.73   20.13  4430.2   20.07
 4477.86   14.99 4549.36   15.05 4597.02   17.39 4712.22   16.64 4806.21   12.83
 4853.39    9.19 4883.53    9.56 4926.81     1.2 5082.25     1.2 5123.13    7.75
 5168.55    8.76 5198.56    15.4 5243.57   16.74 5260.98   16.67 5288.59    13.5
 5393.61   12.22 5450.59    7.95 5543.63     8.7 5577.66    9.99 5601.34    9.58
#Mann= 3 ,-1 , 0
 4114.72     .07       0 4883.53    .027       0 5123.13     .07       0
#Block Obstruct= 1 ,-1
 4108.78 4241.55   20.64
Bank Sta=4883.53,5123.13
XS Rating Curve= 0
Exp/Cntr=.3,.1

Type RM Length L Ch R = 1 ,962.088 ,116.71,962.09,73.25
XS GIS Cut Line= 4
     3174353.365    13835377.833     3173635.611     13834645.43
     3173371.946    13834261.651     3173155.155    13833511.672
#Sta/Elev= 30
 3709.63   20.63 3753.73   11.51 3802.84    5.12 3861.55    1.87  3994.7     3.1
 4075.44    1.67 4168.45    5.12 4240.83    5.46 4274.16    3.61 4292.42    5.11
 4361.16    2.18 4406.33     6.3 4445.17    5.49 4508.18    7.24 4595.26    5.34
 4741.21    6.42 4845.52    4.27 4926.81     1.2 5082.25     1.2 5093.87    2.91
 5150.54    5.01 5397.56   10.51 5417.98   12.38 5585.15   11.18 5662.41   17.62
 5678.67   24.12 5724.48   27.93 5767.95   26.63 5877.02   16.88 5981.41   15.78
#Mann= 3 ,-1 , 0
 3709.63     .07       0 4845.52    .027       0 5150.54     .07       0
#XS Ineff= 1 ,-1
    3795    4399    4.77
Permanent Ineff=
       F
Bank Sta=4845.52,5150.54
XS Rating Curve= 0
Exp/Cntr=.3,.1

Chan Stop Cuts=-1

--- G110_00_00.g02 (geometry) ---

Geom Title=G110-00-00 June 2007 (Floodway)
Version=Version 3.0.1  Mar 2001

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
River Reach=G110-00-00       ,G110-00-00_0010